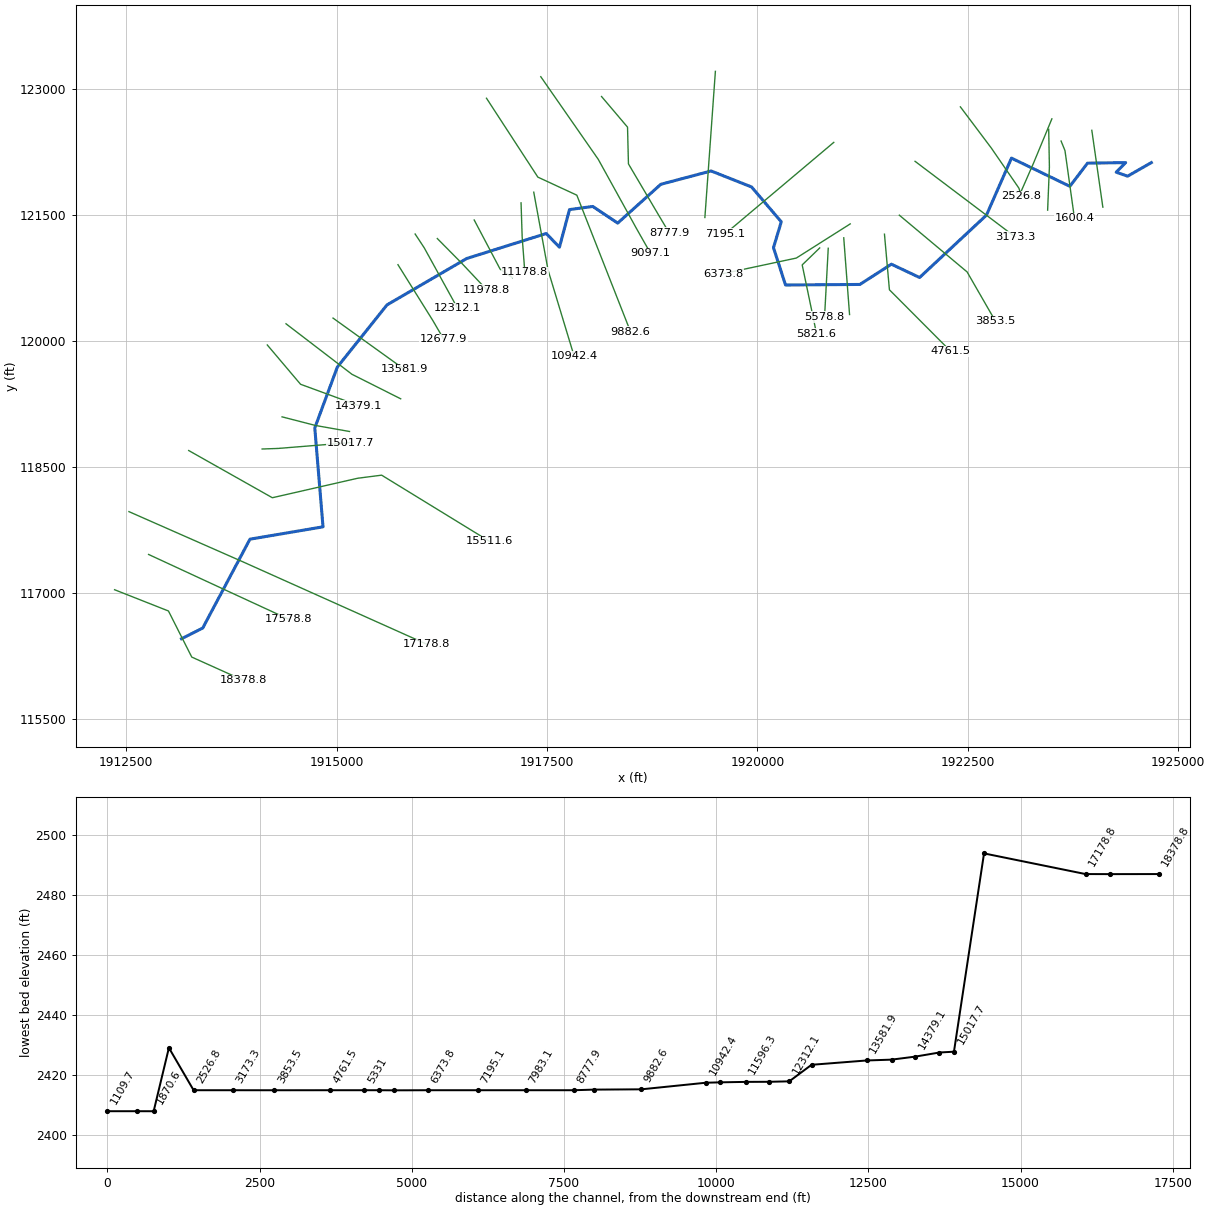
--- NrtFkBrsh.prj (project) ---

Proj Title=NrtFkBrsh
Current Plan=p01
Default Exp/Contr=0,0
English Units
Geom File=g01
Flow File=f01
Plan File=p01
BEGIN DESCRIPTION:
END DESCRIPTION:
DSS Export Rating Curves= 0
DSS Export Rating Curve Sorted= 0
DSS Export Volume Flow Curves= 0
DXF OffsetX= 0
DXF OffsetY= 0
DXF ScaleX= 0
DXF ScaleY= 0

--- NrtFkBrsh.p01 (plan) ---

Plan Title=Floodplain
Program Version=4.00
Geom File=g01
Flow File=f01
K Sum by GR=0
Std Step Tol=0.01
Critical Tol=0.01
Num of Std Step Trials=20
Max Error Tol=0.3
Flow Tol Ratio=0.001
Split Flow NTrial=30
Split Flow Tol=0.02
Split Flow Ratio=0.02
Log Output Level=0
Friction Slope Method=1
Unsteady Friction Slope Method=2
Unsteady Bridges Friction Slope Method=1
Global Log Level=0
CheckData=False
Run HTab=0
Run UNet=0
Run PostProcess=0
UNET Theta=0
UNET Theta Warmup=0
UNET ZTol=0
UNET ZSATol=0
UNET MxIter=0
UNET MaxInSteps=0
UNET DtIC=0
UNET DtMin=0
UNET MaxCRTS=0
UNET WFStab=0
UNET SFStab=0
UNET WFX=0
UNET SFX=0
UNET DSS MLevel=0
UNET DZMax Abort=0
UNET Convert EG Bridges=0
UNET Use Existing IB Tables=0
UNET Froude Limit=0
UNET Froude Power=0
Write IC File=0
Echo Input=False
Echo Output=False
Write Detailed=0

--- NrtFkBrsh.f01 (steady flow) ---

Flow Title=NFF Regression Equation
Program Version=4.00
Number of Profiles=1
Profile Names=P100yr
River Rch & RM=NrtFkBrsh,Main      ,18378.8
510.8924
River Rch & RM=NrtFkBrsh,Main      ,17578.8
558.0776
River Rch & RM=NrtFkBrsh,Main      ,17178.8
592.3183
River Rch & RM=NrtFkBrsh,Main      ,15511.6
655.4782
River Rch & RM=NrtFkBrsh,Main      ,13992.7
672.9647
River Rch & RM=NrtFkBrsh,Main      ,13581.9
1067.679
River Rch & RM=NrtFkBrsh,Main      ,9882.6
1136.160
River Rch & RM=NrtFkBrsh,Main      ,9097.1
1526.684
River Rch & RM=NrtFkBrsh,Main      ,8777.9
1611.316
River Rch & RM=NrtFkBrsh,Main      ,7983.1
1941.107
Boundary for River Rch & Prof#=NrtFkBrsh,Main      ,1
Up Type=0
Dn Type=3
Dn Slope=0.005322

--- NrtFkBrsh.g01 (geometry) ---

Geom Title=USGS 3m DEM
Program Version=4.10

River Reach=NrtFkBrsh       ,Main
Reach XY= 30
     1913157.098      116451.752     1913408.857      116578.877
     1913969.945      117636.661     1914838.076      117783.558
     1914740.422      118960.726     1915008.187      119685.161
     1915598.399      120425.299     1916545.784      120977.459
     1917490.739      121274.623     1917647.403      121111.742
     1917766.765      121559.353     1918043.756      121597.026
     1918339.956      121398.959     1918851.745      121860.396
     1919449.834      122019.325     1919930.441      121828.814
      1920283.34       121414.38     1920190.848      121106.125
     1920333.965      120661.966     1921217.592      120668.631
     1921591.692       120909.64     1921927.056      120751.167
     1922721.235      121493.126     1923018.918      122172.264
     1923712.375      121836.537     1923922.449       122112.25
     1924375.236      122118.866     1924263.333      122004.476
     1924398.395      121957.228     1924680.654      122118.799

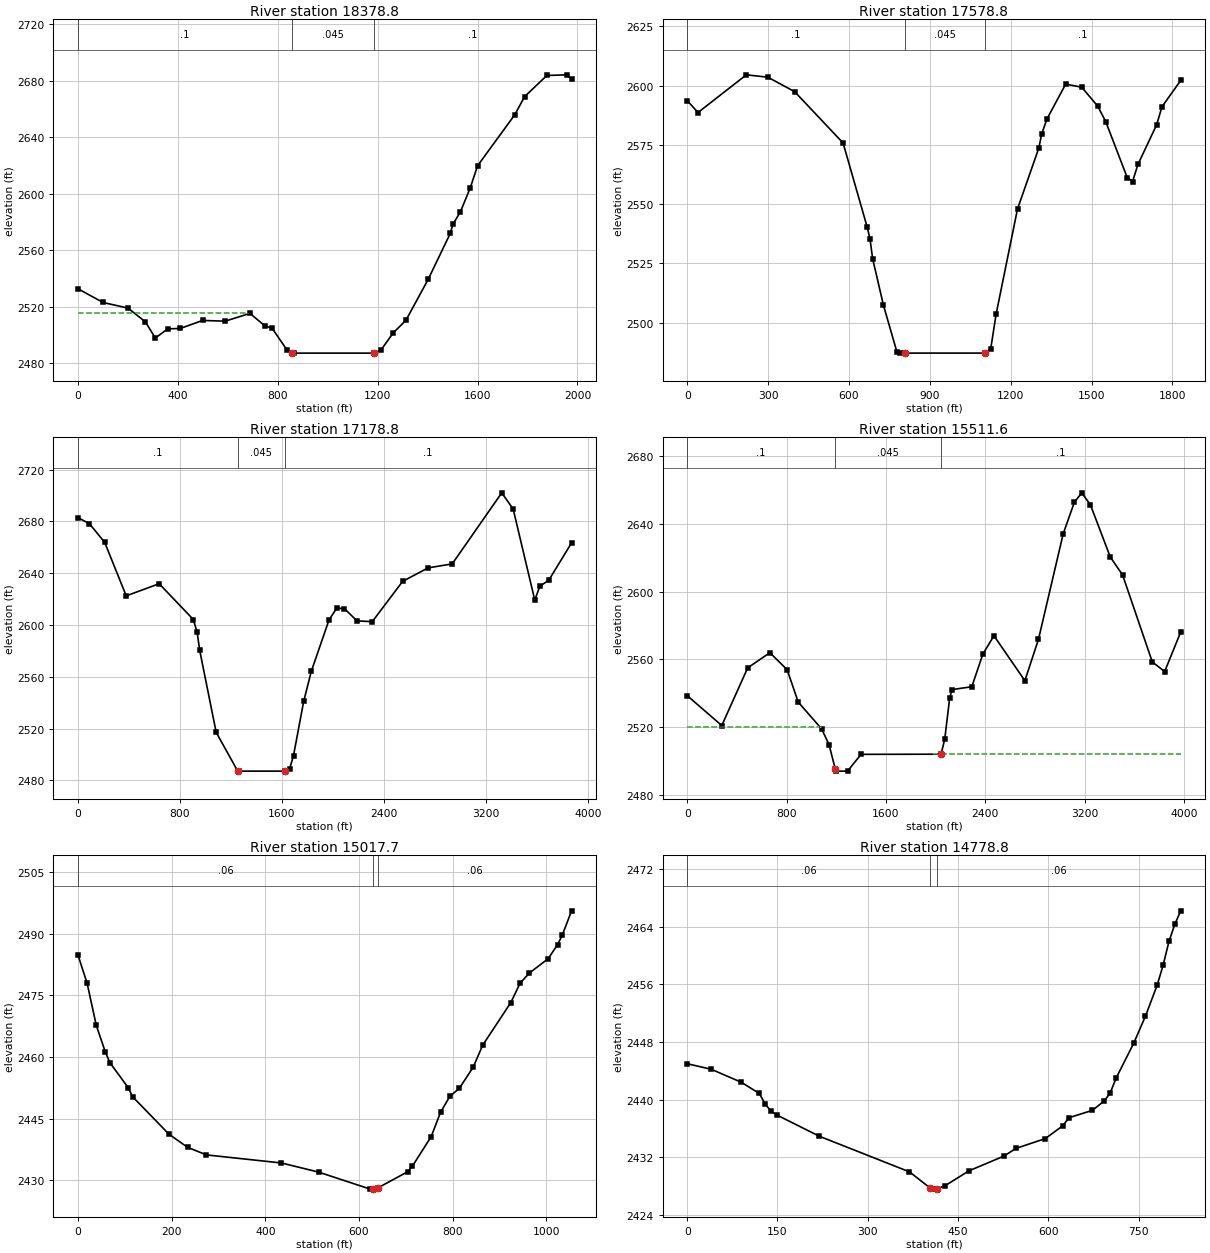
Type RM Length L Ch R = 1 ,18378.8 ,785.4,800,814.7
XS GIS Cut Line= 5
      1912361.35      117035.044     1913001.548      116781.987
     1913166.025      116456.259      1913278.51      116233.495
     1913892.449        115956.5
#Sta/Elev= 30
       0  2532.6    99.8 2522.95   199.5 2518.99   269.4 2509.28   309.3 2497.78
   359.2 2504.29     409 2504.55   498.8 2510.24   588.6 2509.71   688.4 2515.23
   747.6 2506.44   777.2  2504.7   836.3  2489.4     856 2487.17   865.9  2487.1
  1183.1  2487.1    1213 2489.33  1262.9  2501.6  1312.8 2510.27  1401.9 2539.26
    1491 2572.01    1501 2578.26  1530.7 2586.94  1570.3 2603.94    1600 2619.74
  1748.6 2655.74  1788.2 2668.62  1877.3 2683.61  1956.6 2684.07  1976.4  2681.2
#Mann= 3 , 0 , 0
       0      .1       0     856    .045       0  1183.1      .1       0
#XS Ineff= 2 , 0
          680.92 2515.67
Permanent Ineff=
       F       F
Bank Sta=856,1183.1
XS Rating Curve= 0 ,0
Exp/Cntr=0.3,0.1

Type RM Length L Ch R = 1 ,17578.8 ,399.5,400,400.3
XS GIS Cut Line= 3
     1912765.126       117455.08     1913669.433       117035.56
     1914426.301      116685.466
#Sta/Elev= 30
       0 2593.64    39.9 2588.64   219.3 2604.55   299.1 2603.55   398.8 2597.41
   578.2 2575.77   667.9 2540.12   677.9 2535.35   687.8 2526.94   727.7 2507.39
   777.6 2487.67   787.5 2487.08   807.5  2487.1  1106.1  2487.1  1125.9 2488.93
  1145.8  2503.5  1225.2 2547.92  1304.6 2573.74  1314.6 2579.47  1334.4 2585.89
  1403.9 2600.62  1463.5 2599.32    1523  2591.3  1552.8 2584.72  1632.2 2561.21
  1652.1  2559.5    1672 2566.72  1741.4 2583.46  1761.3  2591.1  1830.8 2602.19
#Mann= 3 , 0 , 0
       0      .1       0   807.5    .045       0  1106.1      .1       0
Bank Sta=807.5,1106.1
XS Rating Curve= 0 ,0
Exp/Cntr=0.3,0.1

Type RM Length L Ch R = 1 ,17178.8 ,1650.3,1667.2,1681.3
XS GIS Cut Line= 3
     1912532.074      117964.543     1913878.048      117370.704
     1916068.507      116387.375
#Sta/Elev= 30
       0  2682.9    89.5 2678.18   208.7 2663.81   377.7 2622.49   636.2 2631.88
   904.6 2604.18   934.4  2594.2   954.3 2580.36  1083.5 2517.07  1252.5 2487.12
  1262.4  2487.1  1620.6  2487.1  1660.4 2489.03  1690.3 2499.14    1770 2540.94
  1829.8 2564.17  1969.3 2604.01  2029.1 2612.92  2088.8 2612.72  2188.5 2603.16
    2308 2602.56  2547.1 2633.74  2746.4 2644.09  2935.7  2647.2  3324.2 2702.08
  3413.9 2689.52  3583.3 2619.24  3623.1 2629.96  3692.9 2634.52  3872.2 2663.43
#Mann= 3 , 0 , 0
       0      .1       0  1252.5    .045       0  1620.6      .1       0
Bank Sta=1252.5,1620.6
XS Rating Curve= 0 ,0
Exp/Cntr=0.3,0.1

Type RM Length L Ch R = 1 ,15511.6 ,496.9,493.9,490.8
XS GIS Cut Line= 5
     1913242.159      118691.877     1914236.072      118129.992
     1915250.028      118361.908     1915534.756      118398.595
     1916815.982      117611.419
#Sta/Elev= 30
       0  2538.6     278 2520.93   486.5 2555.03   665.2 2563.97   804.2 2553.94
   893.5 2534.76  1082.2 2518.92  1141.7 2509.61  1191.3  2495.3  1201.2 2493.99
  1290.3    2494  1399.3 2503.91  2043.2    2504  2072.9 2512.86  2112.5 2537.19
  2132.4  2542.2  2290.8 2543.86  2379.9  2563.2    2469    2574  2717.9 2547.44
  2827.5  2571.9  3026.6 2634.29  3116.3 2652.88    3176 2658.47  3245.7 2651.37
  3405.1 2620.61  3504.6 2609.91  3743.6 2558.56  3843.2 2552.83  3972.7 2576.26
#Mann= 3 , 0 , 0
       0      .1       0  1191.3    .045       0  2043.2      .1       0
#XS Ineff= 2 , 0
         1072.82 2519.88 1981.05         2504.26
Permanent Ineff=
       F       F
Bank Sta=1191.3,2043.2
XS Rating Curve= 0 ,0
Exp/Cntr=0.3,0.1

Type RM Length L Ch R = 1 ,15017.7 ,245.9,238.8,233.4
XS GIS Cut Line= 3
     1914114.136      118709.928     1914308.151       118716.94
     1915165.239      118786.538
#Sta/Elev= 30
       0 2484.74    19.4 2477.91    38.8 2467.72    58.2 2461.21      68 2458.62
   106.8 2452.58   116.5 2450.34   194.1 2441.22   234.1 2438.01   274.1 2436.18
   434.1 2434.22   514.1 2431.98   624.1 2427.85     629 2427.87     641  2428.2
   704.1 2432.09   714.1 2433.46   754.1 2440.63   774.1 2446.53   794.1 2450.48
   814.1 2452.35   844.1 2457.59   864.1 2462.88   924.1 2473.24   944.1 2477.99
   964.1 2480.47  1004.1 2483.95    1024 2487.35    1034 2489.64    1054 2495.59
#Mann= 3 , 0 , 0
       0     .06       0     629    .045       0     641     .06       0
Bank Sta=629,641
XS Rating Curve= 0 ,0
Exp/Cntr=0.3,0.1

Type RM Length L Ch R = 1 ,14778.8 ,401.8,399.7,395.9
XS GIS Cut Line= 3
     1914351.826      119092.616     1914748.044      118990.222
     1915152.738      118918.511
#Sta/Elev= 30
       0 2444.99    39.9 2444.22    89.8 2442.42   119.8 2440.86   129.8 2439.35
   139.7 2438.38   149.7 2437.84   219.6 2434.92   369.3 2429.98   403.2 2427.77
   409.2 2427.58   415.2 2427.64   428.8 2428.07     468 2430.11   526.7 2432.18
   546.2 2433.23   595.2  2434.6   624.5  2436.4   634.3 2437.49   673.4 2438.52
     693 2439.82   702.8  2440.9   712.6 2442.96     742 2447.83   761.5 2451.58
   781.1 2455.92   790.9 2458.67   800.7 2461.99   810.4 2464.37   820.2 2466.22
#Mann= 3 , 0 , 0
       0     .06       0   403.2    .045       0   415.2     .06       0
Bank Sta=403.2,415.2
XS Rating Curve= 0 ,0
Exp/Cntr=0.3,0.1

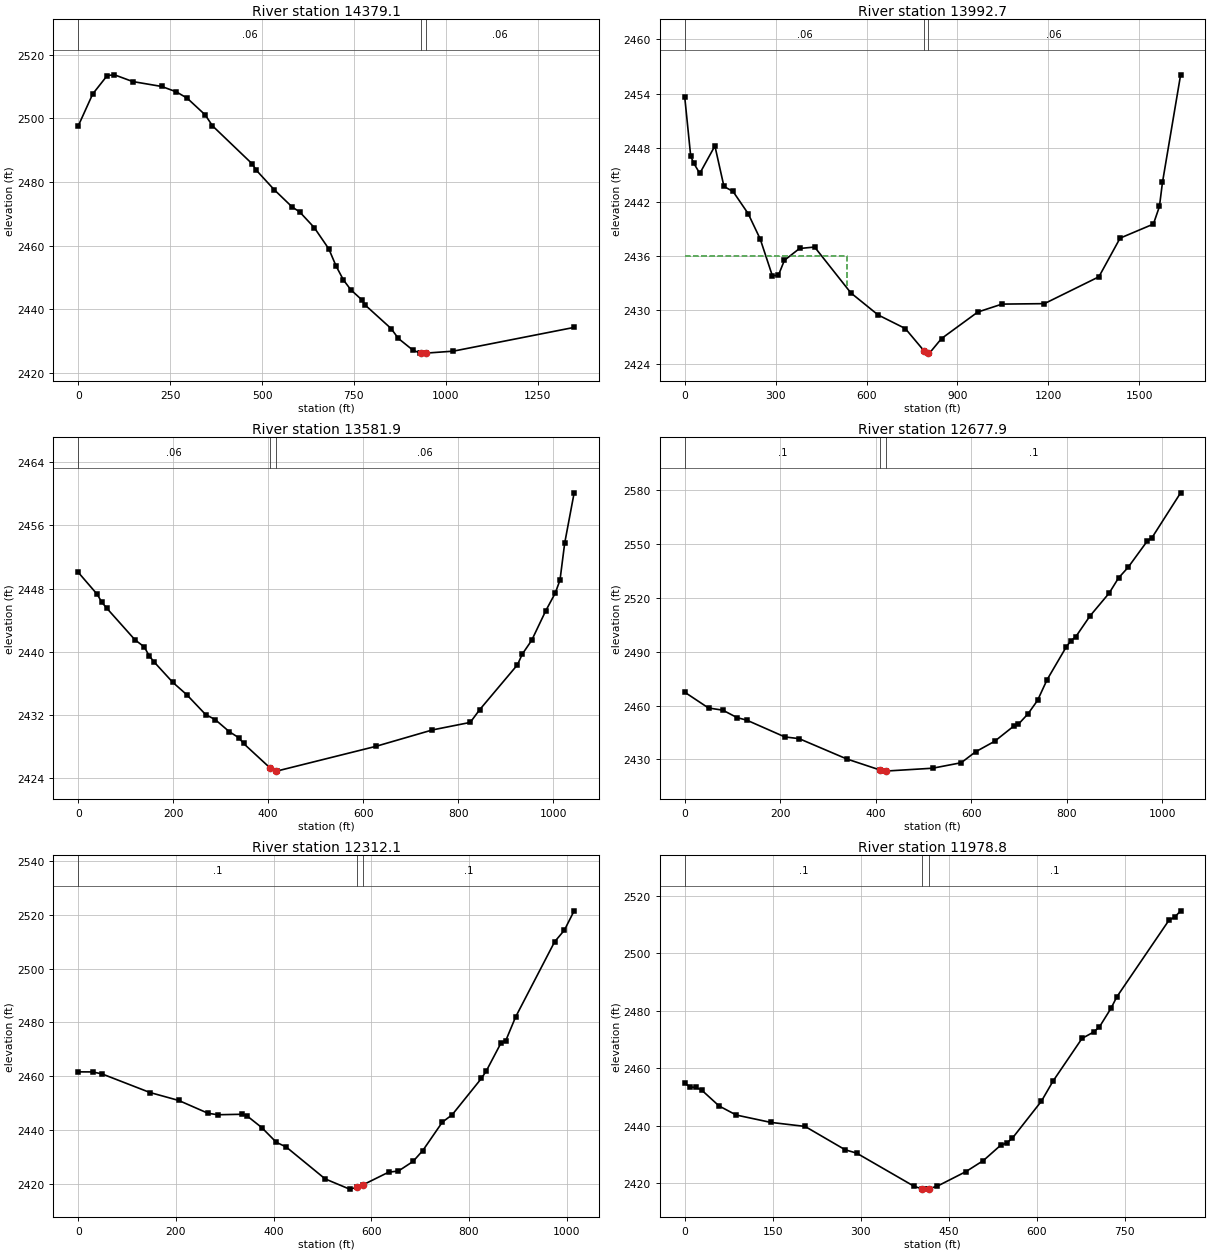
Type RM Length L Ch R = 1 ,14379.1 ,392.7,386.3,379.9
XS GIS Cut Line= 3
     1914176.262      119948.039     1914571.304      119480.533
     1915263.206      119226.261
#Sta/Elev= 30
       0 2497.61    39.5 2507.69      79 2513.48    98.7  2513.7   148.1 2511.59
   227.1 2510.04   266.5 2508.37   296.2 2506.38   345.5  2501.1   365.3 2497.66
   473.8 2485.65   483.7 2483.81   533.1 2477.59   582.4 2472.11   602.2 2470.63
     642 2465.69   681.8 2458.96   701.7 2453.53   721.6  2449.2   741.6 2446.12
   771.4 2442.97   781.4 2441.24   851.1 2433.94   871.1  2430.8   910.9  2427.1
   930.8  2426.2   933.7  2426.2   945.7  2426.2  1020.5 2426.82  1349.2 2434.29
#Mann= 3 , 0 , 0
       0     .06       0   933.7    .045       0   945.7     .06       0
Bank Sta=933.7,945.7
XS Rating Curve= 0 ,0
Exp/Cntr=0.3,0.1

Type RM Length L Ch R = 1 ,13992.7 ,410,410.8,411.6
XS GIS Cut Line= 3
     1914398.327      120200.492       1915181.4      119599.747
     1915761.107      119307.556
#Sta/Elev= 30
       0 2453.67    19.9 2447.05    29.9 2446.28    49.8 2445.14    99.7 2448.19
   129.6 2443.69   159.5 2443.14   209.4 2440.68   249.2 2437.86   289.1  2433.8
     309 2433.82     329  2435.5   378.8 2436.81   428.7 2436.97   548.3 2431.88
     638 2429.44   727.8 2427.93   789.9 2425.44   801.9 2425.21   807.5  2425.2
   847.4 2426.82     967 2429.76  1046.9 2430.64  1186.7 2430.69  1366.5 2433.67
  1436.4 2437.96  1546.3 2439.52  1566.2 2441.47  1576.2 2444.14  1636.1 2456.08
#Mann= 3 , 0 , 0
       0     .06       0   789.9    .045       0   801.9     .06       0
#XS Ineff= 2 , 0
          536.41 2435.95
Permanent Ineff=
       F       F
Bank Sta=789.9,801.9
XS Rating Curve= 0 ,0
Exp/Cntr=0.3,0.1

Type RM Length L Ch R = 1 ,13581.9 ,912.3,903.8,894.7
XS GIS Cut Line= 2
     1914956.821      120268.455     1915804.351      119658.331
#Sta/Elev= 30
       0 2450.06    39.8 2447.29    49.7 2446.28    59.7 2445.55   119.4 2441.53
   139.2 2440.62   149.2 2439.52   159.1 2438.77   198.9 2436.16   228.8 2434.57
   268.5 2432.06   288.4 2431.44   318.3  2429.9   338.2 2429.14   348.1 2428.42
   404.6 2425.29   416.6 2424.94   417.7 2424.92   626.6 2428.05   745.9 2430.13
   825.5 2431.08   845.4 2432.69     925 2438.37   934.9  2439.7   954.8 2441.45
   984.6 2445.21  1004.5 2447.43  1014.5 2449.08  1024.4 2453.76  1044.3 2460.11
#Mann= 3 , 0 , 0
       0     .06       0   404.6    .045       0   416.6     .06       0
Bank Sta=404.6,416.6
XS Rating Curve= 0 ,0
Exp/Cntr=0.3,0.1

Type RM Length L Ch R = 1 ,12677.9 ,367,365.8,364.6
XS GIS Cut Line= 3
     1915728.769      120903.671     1916140.955      120242.714
     1916271.857      120018.311
#Sta/Elev= 30
       0 2467.44    49.9 2458.62    79.9 2457.42   109.8 2453.26   129.8 2451.89
   209.7 2442.53   239.7 2441.56   339.5 2430.25   409.9 2424.04   419.4 2423.48
   421.9 2423.53   519.3  2425.1   579.2 2428.16   609.2 2434.22   649.1 2440.08
   689.1 2448.52   699.1 2449.65     719 2455.36     739 2462.83     759 2474.36
   798.9  2492.5   808.9 2496.06   818.9 2498.22   848.9 2509.86   888.9 2522.54
   908.8 2531.07   928.8 2536.95   968.8 2551.55   978.8 2553.48  1038.7 2578.42
#Mann= 3 , 0 , 0
       0      .1       0   409.9    .045       0   421.9      .1       0
Bank Sta=409.9,421.9
XS Rating Curve= 0 ,0
Exp/Cntr=0.3,0.1

Type RM Length L Ch R = 1 ,12312.1 ,326.2,332.9,339
XS GIS Cut Line= 3
     1915932.915      121268.889     1916040.441      121105.262
     1916435.862      120387.231
#Sta/Elev= 30
       0  2461.6    29.4 2461.58      49 2460.82   146.8 2453.92   205.8 2450.96
   265.8 2446.19   285.8 2445.64   335.8 2445.82   345.7 2445.21   375.7 2440.89
   405.7 2435.38   425.7 2433.67   505.7 2421.76   555.7 2417.96   570.8 2418.63
   582.8 2419.53   635.6 2424.27   655.6 2424.69   685.6 2428.26   705.6 2432.33
   745.6 2442.89   765.6 2445.61   825.6 2459.16   835.6 2461.94   865.6 2472.31
   875.6 2473.27   895.6 2482.02   975.5    2510   995.5 2514.34  1015.5 2521.53
#Mann= 3 , 0 , 0
       0      .1       0   570.8    .045       0   582.8      .1       0
Bank Sta=570.8,582.8
XS Rating Curve= 0 ,0
Exp/Cntr=0.3,0.1

Type RM Length L Ch R = 1 ,11978.8 ,388.8,382.6,376.9
XS GIS Cut Line= 3
     1916196.161      121215.114      1916484.61      120923.218
     1916782.463      120606.216
#Sta/Elev= 30
       0 2454.74     9.8  2453.4    19.5 2453.28    29.3 2452.29    58.6 2446.82
    87.9 2443.65   146.6 2441.09   205.2 2439.68   273.6 2431.53   293.1 2430.37
   390.8 2418.83   404.4 2417.89   410.4 2417.81   416.4 2418.02   430.1 2418.78
   479.6 2423.94   509.2 2427.78   538.9 2433.16   548.8 2433.86   558.7  2435.6
   608.1 2448.48   627.9 2455.48   677.3 2470.36   697.1 2472.59     707 2474.39
   726.7 2480.86   736.6 2484.85   825.6 2511.61   835.5 2512.71   845.4 2514.87
#Mann= 3 , 0 , 0
       0      .1       0   404.4    .045       0   416.4      .1       0
Bank Sta=404.4,416.4
XS Rating Curve= 0 ,0
Exp/Cntr=0.3,0.1

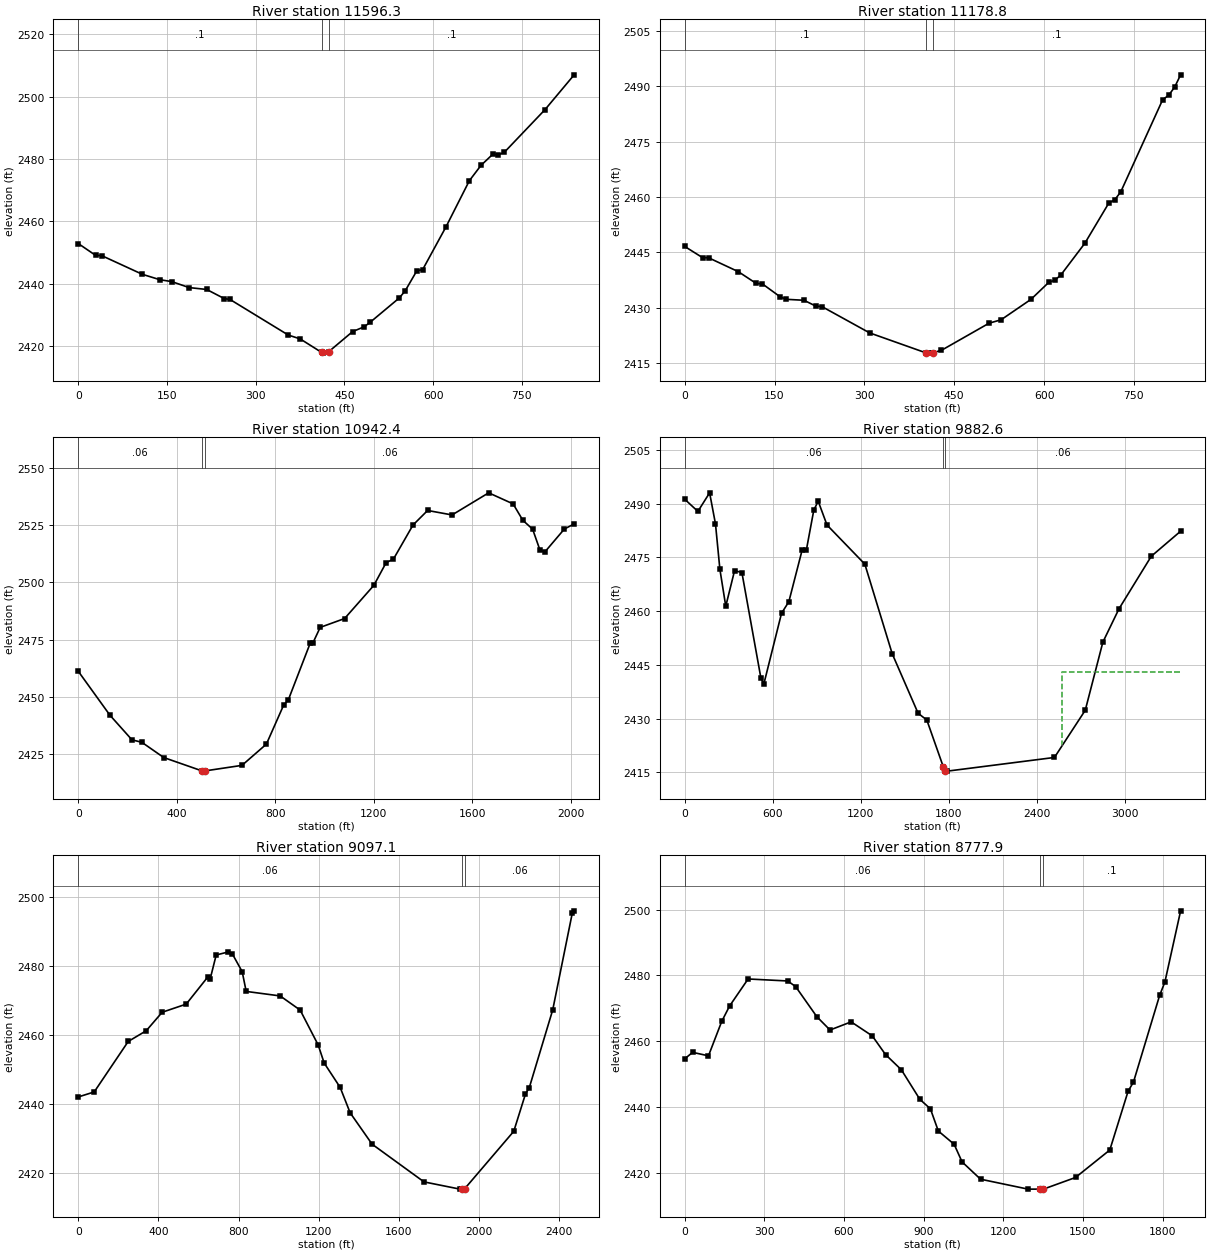
Type RM Length L Ch R = 1 ,11596.3 ,426.9,417.4,408.9
XS GIS Cut Line= 3
     1916634.762      121435.496     1916942.728      120850.471
     1917088.354      120749.725
#Sta/Elev= 30
       0 2452.94    29.6 2449.11    39.5 2449.07   108.5 2443.05   138.2 2441.32
   157.9 2440.73   187.5  2438.8   217.1  2438.2   246.7 2435.29   256.6 2434.99
   355.2 2423.56     375 2422.36   411.5    2418   414.4 2417.78   423.5 2418.26
   463.8 2424.69   483.5 2426.24   493.4 2427.67   542.7 2435.48   552.6 2437.75
   572.3 2444.19   582.2 2444.58   621.7 2458.32   661.1 2473.09   680.8 2478.01
   700.5 2481.54   710.3 2481.39   720.2  2482.2     789 2495.89   838.2 2507.04
#Mann= 3 , 0 , 0
       0      .1       0   411.5    .045       0   423.5      .1       0
Bank Sta=411.5,423.5
XS Rating Curve= 0 ,0
Exp/Cntr=0.3,0.1

Type RM Length L Ch R = 1 ,11178.8 ,233.2,236.3,238.5
XS GIS Cut Line= 3
     1917191.382      121639.536     1917204.741      121231.447
     1917236.245      120813.064
#Sta/Elev= 30
       0 2446.56    29.9 2443.51    39.8 2443.49    89.6 2439.71   119.5 2436.51
   129.5 2436.43   159.3 2432.91   169.3 2432.22   199.2 2431.96   219.1 2430.36
     229 2430.26   308.7 2423.12   402.3 2417.73   408.3 2417.63   414.3 2417.77
   428.3 2418.36   508.2 2425.75   528.2 2426.67   578.1 2432.21   608.1 2436.86
   618.1  2437.4   628.1 2438.85     668 2447.41     708 2458.31     718 2459.21
     728 2461.36   797.9 2486.33   807.9 2487.53   817.9 2489.74   827.9 2493.08
#Mann= 3 , 0 , 0
       0      .1       0   402.3    .045       0   414.3      .1       0
Bank Sta=402.3,414.3
XS Rating Curve= 0 ,0
Exp/Cntr=0.3,0.1

Type RM Length L Ch R = 1 ,10942.4 ,1053.2,1059.7,1039.1
XS GIS Cut Line= 3
     1917342.153      121767.075     1917512.208       120839.66
     1917822.262      119814.478
#Sta/Elev= 30
       0 2461.18     129 2441.92   218.4 2431.16     258 2430.13   347.4 2423.44
   504.1 2417.55   506.2  2417.5   516.1 2417.62     665 2420.02   764.2 2429.31
   833.7 2446.24   853.6 2448.76   942.9 2473.67   952.8 2473.48   982.6 2480.33
  1081.7  2484.2  1200.7 2498.73  1250.3 2508.62  1280.1 2510.18  1359.4 2525.06
  1418.9 2531.44  1518.1 2529.48  1666.8 2539.15    1766 2534.31  1805.7 2527.12
  1845.3 2523.26  1875.1  2514.1  1894.9  2513.3  1974.2 2523.34  2013.9 2525.56
#Mann= 3 , 0 , 0
       0     .06       0   504.1    .045       0   516.1     .06       0
Bank Sta=504.1,516.1
XS Rating Curve= 0 ,0
Exp/Cntr=0.3,0.1

Type RM Length L Ch R = 1 ,9882.6  ,793.3,785.3,790
XS GIS Cut Line= 4
     1916780.659      122885.057     1917391.011      121945.996
     1917854.052      121731.252       1918493.6      120102.462
#Sta/Elev= 30
       0 2491.27      90 2487.86     170 2493.05     210 2484.34     240 2471.68
     280 2461.37     340 2471.32     390 2470.78     520 2441.19     540 2439.72
     660 2459.39     710 2462.64     800 2476.98     830 2477.21     880 2488.21
     910 2490.71     970 2484.06    1228 2473.12  1414.4  2448.1  1591.1 2431.46
  1650.4 2429.58  1763.4 2416.42  1775.4 2415.43  1790.4  2415.3  2520.3 2419.12
  2730.3 2432.31  2850.3 2451.34  2960.3 2460.66  3180.3 2475.33  3380.2 2482.33
#Mann= 3 , 0 , 0
       0     .06       0  1763.4    .045       0  1775.4     .06       0
#XS Ineff= 2 , 0
                         2569.89         2442.88
Permanent Ineff=
       F       F
Bank Sta=1763.4,1775.4
XS Rating Curve= 0 ,0
Exp/Cntr=0.3,0.1

Type RM Length L Ch R = 1 ,9097.1  ,318.6,319.1,319.6
XS GIS Cut Line= 4
     1917425.817       123141.25     1918108.653      122157.771
     1918565.849      121328.788     1918728.892      121041.272
#Sta/Elev= 30
       0 2441.97    79.8 2443.43   249.4 2458.09   339.2  2461.2     419 2466.58
   538.8 2468.94   648.5 2476.96   658.5 2476.26   688.4 2483.21   748.3 2484.09
   768.3 2483.61   818.2 2478.36   838.1 2472.63  1007.7 2471.32  1107.5  2467.2
  1197.3 2457.08  1227.2 2451.83  1306.9 2444.76  1356.7 2437.38  1466.4 2428.25
  1725.4  2417.3  1904.8  2415.2  1916.2 2415.23  1928.2 2415.31  2173.2    2432
  2231.5 2442.82  2250.9 2444.72  2367.6 2467.28  2464.8 2495.28  2474.5 2496.04
#Mann= 3 , 0 , 0
       0     .06       0  1916.2    .045       0  1928.2     .06       0
Bank Sta=1916.2,1928.2
XS Rating Curve= 0 ,0
Exp/Cntr=0.3,0.1

Type RM Length L Ch R = 1 ,8777.9  ,807.8,794.8,781.8
XS GIS Cut Line= 5
     1918147.646      122905.627     1918456.569      122541.028
      1918467.42      122103.387     1918825.315      121495.337
     1918951.542      121283.206
#Sta/Elev= 30
       0 2454.61    29.9 2456.59    89.6 2455.53   139.4 2465.97   169.2 2470.69
   238.9  2478.9   388.3 2478.29   418.1 2476.57   497.8 2467.43   547.5 2463.38
   627.1 2465.86   706.7 2461.59   756.5 2455.92   816.2 2451.29   885.8 2442.31
   925.6 2439.41   955.4 2432.67    1015 2428.64  1044.8 2423.29  1114.4 2418.02
  1293.3    2415  1339.3    2415  1351.3    2415  1472.2 2418.54  1601.3 2426.89
  1670.6 2444.85  1690.3  2447.5  1789.1 2473.92  1808.8 2477.96  1868.1 2499.62
#Mann= 3 , 0 , 0
       0     .06       0  1339.3    .045       0  1351.3      .1       0
Bank Sta=1339.3,1351.3
XS Rating Curve= 0 ,0
Exp/Cntr=0.3,0.1

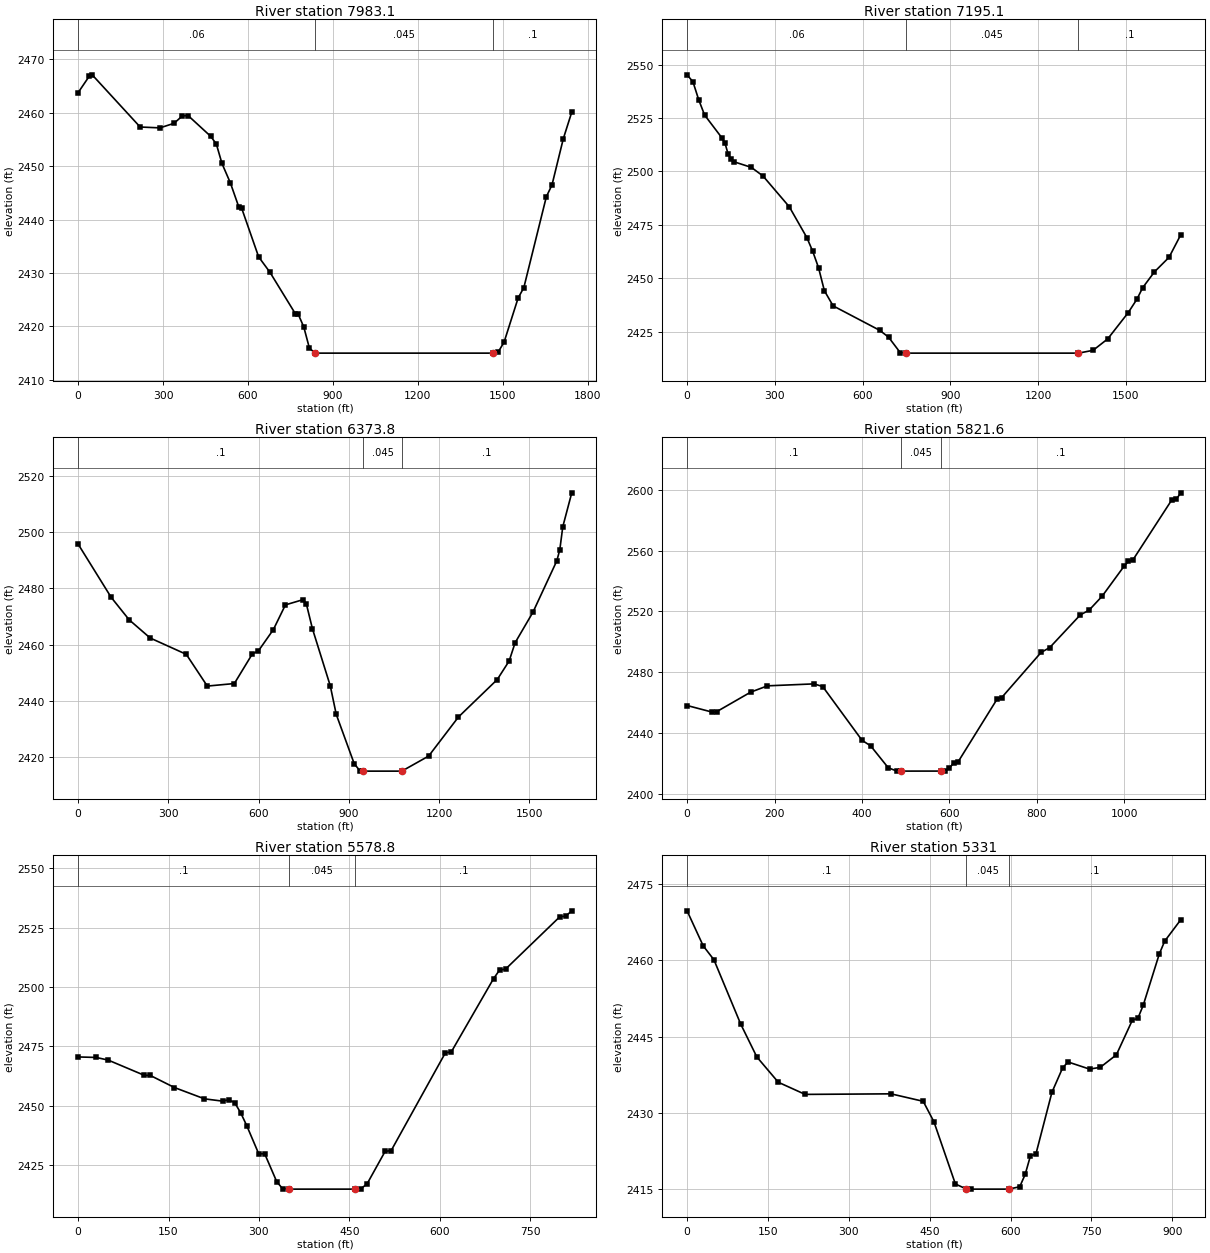
Type RM Length L Ch R = 1 ,7983.1  ,804.7,788.1,771.4
XS GIS Cut Line= 2
     1919500.562       123204.75     1919375.803      121465.534
#Sta/Elev= 30
       0 2463.76    39.9 2466.88    49.8  2467.1   219.2 2457.33     289 2457.17
   338.8 2458.02   368.7 2459.43   388.6 2459.47   468.3 2455.59   488.2 2454.16
   508.2  2450.5     538 2446.85   567.9 2442.32   577.9 2442.11   637.7 2433.02
   677.6 2430.14   767.2 2422.39   777.2 2422.32   797.1 2419.91     817 2415.94
     837    2415  1464.7    2415  1484.6 2415.28  1504.6 2417.05  1554.4 2425.34
  1574.3 2427.24    1654 2444.29  1673.9 2446.49  1713.8 2455.13  1743.7 2460.12
#Mann= 3 , 0 , 0
       0     .06       0     837    .045       0  1464.7      .1       0
Bank Sta=837,1464.7
XS Rating Curve= 0 ,0
Exp/Cntr=0.3,0.1

Type RM Length L Ch R = 1 ,7195.1  ,833,821.3,809.4
XS GIS Cut Line= 2
     1920907.188      122359.592     1919617.562       121271.46
#Sta/Elev= 30
       0 2545.19      20 2541.96    39.9 2533.47    59.9 2526.38   119.8 2515.57
   129.8 2513.12   139.8 2508.37   149.8 2505.82   159.8 2504.54   219.7 2501.89
   259.6 2497.85   349.4 2483.46   409.4 2469.05   429.3 2462.68   449.3 2454.98
   469.3  2444.2   499.2 2437.11     659 2425.63   688.9 2422.43   728.9 2415.18
   748.8    2415  1337.9    2415  1387.8 2416.31  1437.8 2421.66  1507.6 2433.88
  1537.6 2440.22  1557.6 2445.66  1597.5 2453.01  1647.4 2459.82  1687.4 2470.34
#Mann= 3 , 0 , 0
       0     .06       0   748.8    .045       0  1337.9      .1       0
Bank Sta=748.8,1337.9
XS Rating Curve= 0 ,0
Exp/Cntr=0.3,0.1

Type RM Length L Ch R = 1 ,6373.8  ,518.2,552.1,586
XS GIS Cut Line= 3
     1921102.828      121389.272     1920461.878      120982.542
     1919599.373      120798.376
#Sta/Elev= 30
       0  2495.7   109.9 2476.78   169.8 2468.78   239.7 2462.31   359.6 2456.52
   429.5 2445.23   519.4 2446.13   579.3 2456.67   599.3 2457.72   649.2 2465.32
   689.2 2474.09   749.1 2475.99   759.1 2474.31   778.9 2465.66   838.4 2445.29
   858.2 2435.16   917.7  2417.7   937.5    2415   947.4    2415  1076.2    2415
  1165.4 2420.36  1264.5 2434.25  1393.3 2447.54    1433 2454.16  1452.8 2460.64
  1512.2 2471.51  1591.5 2489.77  1601.4 2493.73  1611.3 2501.88  1641.1 2513.92
#Mann= 3 , 0 , 0
       0      .1       0   947.4    .045       0  1076.2      .1       0
Bank Sta=947.4,1076.2
XS Rating Curve= 0 ,0
Exp/Cntr=0.3,0.1

Type RM Length L Ch R = 1 ,5821.6  ,248.3,242.8,237.3
XS GIS Cut Line= 3
     1920740.306      121103.194     1920532.003      120901.196
     1920703.102      120080.287
#Sta/Elev= 30
       0 2458.14      58 2453.74    67.7 2454.08   145.1 2466.89   183.8 2471.08
   290.2 2472.37   310.1 2470.61     400 2435.25   419.9 2431.54   459.9 2417.19
   479.8 2414.96   489.8 2414.98   579.7 2414.99   589.6 2415.14   599.6 2416.85
   609.6 2420.41   619.6 2421.03   709.4 2462.61   719.4 2463.38   809.3 2493.03
   829.2 2496.26   899.1 2517.77   919.1 2520.85     949 2530.06   998.9  2549.7
  1008.9 2552.95  1018.9 2553.74  1108.7 2593.63  1118.7 2593.88  1128.7 2598.08
#Mann= 3 , 0 , 0
       0      .1       0   489.8    .045       0   579.7      .1       0
Bank Sta=489.8,579.7
XS Rating Curve= 0 ,0
Exp/Cntr=0.3,0.1

Type RM Length L Ch R = 1 ,5578.8  ,245.1,247.8,250.5
XS GIS Cut Line= 3
     1920841.563      121098.825     1920819.554      120689.917
     1920797.685      120281.001
#Sta/Elev= 30
       0 2470.58      30 2470.37    49.9 2469.26   109.9 2462.85   119.8  2462.8
   159.8 2457.72   209.7 2452.96   239.7    2452   249.7 2452.57   259.7 2451.38
   269.7 2447.11   279.7 2441.74   299.6  2429.9   309.6 2429.84   329.6  2418.1
   339.6 2415.08   349.6    2415   459.4    2415   469.4 2415.22   479.4  2417.2
   509.4 2430.89   519.4 2431.21   609.3  2472.3   619.2 2472.72   689.2 2503.48
   699.2 2507.09   709.1  2507.5     799 2529.48     809  2529.8     819 2532.02
#Mann= 3 , 0 , 0
       0      .1       0   349.6    .045       0   459.4      .1       0
Bank Sta=349.6,459.4
XS Rating Curve= 0 ,0
Exp/Cntr=0.3,0.1

Type RM Length L Ch R = 1 ,5331    ,569.7,569.5,569.2
XS GIS Cut Line= 2
      1921025.69      121223.775     1921094.678      120310.644
#Sta/Elev= 30
       0 2469.76    29.9 2462.87    49.8 2460.13    99.5 2447.47   129.4 2441.01
   169.2 2436.03     219 2433.64   378.2 2433.75     438 2432.28   457.9 2428.25
   497.7 2416.01   517.6 2415.05   527.5    2415   597.2    2415   617.1 2415.48
   627.1 2417.88     637 2421.58     647 2421.88   676.8 2434.06   696.8  2438.9
   706.7 2440.02   746.5 2438.62   766.4 2438.96   796.3 2441.42   826.2  2448.3
   836.1 2448.58   846.1 2451.17   875.9 2461.26   885.9 2463.79   915.7    2468
#Mann= 3 , 0 , 0
       0      .1       0   517.6    .045       0   597.2      .1       0
Bank Sta=517.6,597.2
XS Rating Curve= 0 ,0
Exp/Cntr=0.3,0.1

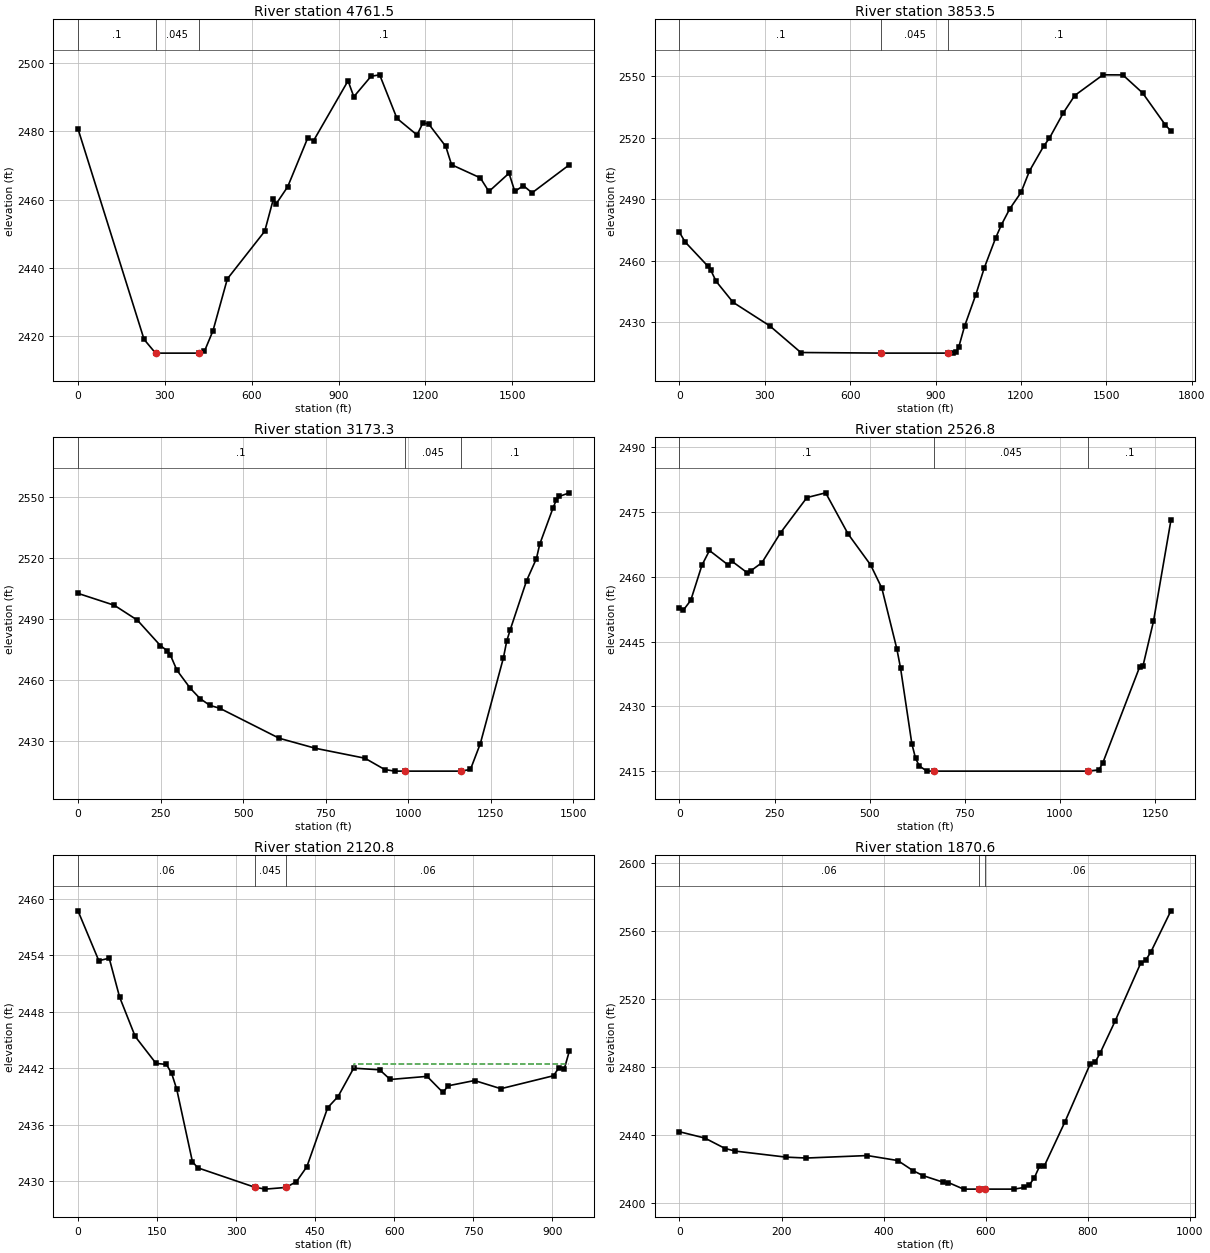
Type RM Length L Ch R = 1 ,4761.5  ,889.7,908,925.7
XS GIS Cut Line= 3
     1921509.558      121267.253     1921568.464      120605.264
      1922296.37       119873.15
#Sta/Elev= 30
       0  2480.7   228.2 2419.02   267.8    2415   416.6    2415   436.5  2415.5
   466.2 2421.56   515.8 2436.75   644.8 2450.69   674.5 2460.06   684.5 2458.74
   724.2 2463.74   793.6 2478.07   813.5 2477.22   932.6 2494.77   952.5  2490.1
    1012 2496.09  1041.8 2496.52  1101.4 2483.77  1170.9  2478.9  1190.7 2482.36
  1210.6 2482.17  1270.1 2475.55    1290 2470.19  1389.3 2466.34    1419 2462.35
  1488.5  2467.7  1508.4 2462.38  1538.2 2464.05    1568 2461.95    1697 2470.18
#Mann= 3 , 0 , 0
       0      .1       0   267.8    .045       0   416.6      .1       0
Bank Sta=267.8,416.6
XS Rating Curve= 0 ,0
Exp/Cntr=0.3,0.1

Type RM Length L Ch R = 1 ,3853.5  ,679.2,680.3,681.4
XS GIS Cut Line= 3
     1921686.041      121493.292     1922491.398       120817.59
     1922828.002      120231.649
#Sta/Elev= 30
       0 2473.85    19.8  2469.2    99.2 2457.47   109.1 2455.67   128.9 2449.98
   188.4 2439.76   317.4 2428.27   426.5 2415.29   709.8    2415   942.2    2415
     962 2414.99   971.9 2415.34   981.8  2418.1  1001.7 2428.01  1041.4 2443.47
  1071.2 2456.56  1110.9 2471.06  1130.8 2477.39  1160.6 2485.31  1200.3 2493.33
  1230.1 2503.82  1279.8 2515.88  1299.7 2519.68  1349.4 2532.23  1389.1 2540.59
  1488.5 2550.67  1558.1 2550.63  1627.6 2541.83  1707.1 2526.32    1727 2523.25
#Mann= 3 , 0 , 0
       0      .1       0   709.8    .045       0   942.2      .1       0
Bank Sta=709.8,942.2
XS Rating Curve= 0 ,0
Exp/Cntr=0.3,0.1

Type RM Length L Ch R = 1 ,3173.3  ,653.5,646.4,639.4
XS GIS Cut Line= 2
     1921873.044      122134.086     1923060.172      121236.474
#Sta/Elev= 30
       0  2502.5   109.9 2496.66   179.8 2489.32   249.7 2476.78   269.7 2474.31
   279.7  2472.2   299.6 2464.68   339.6 2455.89   369.6 2450.73   399.5 2447.36
   429.5 2445.94   609.3 2431.19   719.2 2426.24     869 2421.36   928.9 2415.79
   958.9    2415   988.9    2415  1158.7    2415  1188.6 2415.81  1218.6 2428.59
  1288.5 2470.79  1298.5 2479.04  1308.5 2484.31  1358.4 2508.66  1388.4 2519.62
  1398.4 2526.68  1438.3 2544.37  1448.3 2548.35  1458.3 2550.28  1488.3    2552
#Mann= 3 , 0 , 0
       0      .1       0   988.9    .045       0  1158.7      .1       0
Bank Sta=988.9,1158.7
XS Rating Curve= 0 ,0
Exp/Cntr=0.3,0.1

Type RM Length L Ch R = 1 ,2526.8  ,426.9,405.6,384.3
XS GIS Cut Line= 4
      1922411.61      122782.361     1922778.135      122293.662
     1923106.665      121815.308     1923138.504      121719.798
#Sta/Elev= 30
       0 2452.83     9.8 2452.23    29.6 2454.53    59.1 2462.68    78.8 2466.08
   128.1 2462.72   137.9  2463.6   177.4 2460.97   187.2 2461.35   216.8 2463.26
     266 2470.22     335 2478.33   384.3 2479.43   443.4 2469.89   502.5 2462.74
     532 2457.36   571.5 2443.28   581.3  2438.8   610.9 2421.33   620.7 2417.94
   630.6 2416.21   650.2    2415   669.9    2415  1073.2    2415  1102.7 2415.29
  1112.5 2416.82  1209.5 2439.06  1218.6 2439.38  1246.1 2449.67  1291.9 2473.03
#Mann= 3 , 0 , 0
       0      .1       0   669.9    .045       0  1073.2      .1       0
Bank Sta=669.9,1073.2
XS Rating Curve= 0 ,0
Exp/Cntr=0.3,0.1

Type RM Length L Ch R = 1 ,2120.8  ,242,250.4,258.2
XS GIS Cut Line= 3
     1923498.951       122639.85     1923280.158      122111.101
     1923135.699      121781.509
#Sta/Elev= 30
       0 2458.72    39.5 2453.42    59.2 2453.69    78.9 2449.56   108.5 2445.37
     148 2442.51   167.7  2442.4   177.6 2441.46   187.4 2439.74     217 2432.08
   226.9 2431.42   335.4 2429.35   355.2 2429.15   394.6 2429.33   414.4 2429.95
   434.1 2431.53   473.6  2437.8   493.3 2438.99   522.9    2442   572.2 2441.83
   592.2  2440.8   662.2 2441.13   692.2 2439.42   702.2 2440.13   752.2 2440.69
   802.1 2439.82   902.1  2441.2   912.1 2442.05   922.1 2441.87   932.1 2443.84
#Mann= 3 , 0 , 0
       0     .06       0   335.4    .045       0   394.6     .06       0
#XS Ineff= 2 , 0
                          523.81         2442.47
Permanent Ineff=
       F       F
Bank Sta=335.4,394.6
XS Rating Curve= 0 ,0
Exp/Cntr=0.3,0.1

Type RM Length L Ch R = 1 ,1870.6  ,266.5,270.2,274.2
XS GIS Cut Line= 3
     1923461.083      122515.026     1923469.498      122067.623
      1923448.46      121552.899
#Sta/Elev= 30
       0 2441.76    49.7 2438.04    89.5 2431.88   109.4 2430.37   208.8 2426.82
   248.6 2426.29   367.9 2427.75   427.6 2424.82   457.4 2418.88   477.2 2415.93
   516.8 2412.03   526.7 2411.87   556.5 2407.99     587    2408     599    2408
   655.5 2407.99   675.3 2408.99   685.2 2410.38   695.2 2414.74   705.1 2421.32
     715 2421.84   754.6 2447.28   804.1  2481.4     814 2482.63   823.9 2488.01
   853.7 2507.13   903.2 2540.82   913.1  2542.7     923 2547.34   962.6 2571.78
#Mann= 3 , 0 , 0
       0     .06       0     587    .045       0     599     .06       0
Bank Sta=587,599
XS Rating Curve= 0 ,0
Exp/Cntr=0.3,0.1

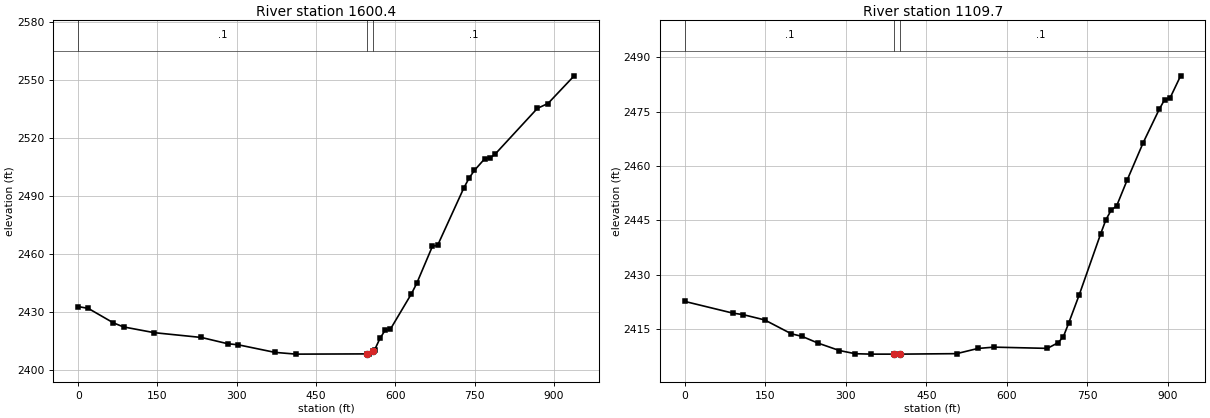
Type RM Length L Ch R = 1 ,1600.4  ,491,490.8,490.8
XS GIS Cut Line= 3
     1923608.157      122375.997      1923654.63       122261.17
      1923767.42      121454.353
#Sta/Elev= 30
       0 2432.64    19.1 2431.69    66.7 2424.18    85.8  2422.1   143.8 2419.12
   233.2 2416.63   282.8 2413.39   302.7 2412.84   372.2 2408.91     412    2408
   546.5 2408.12   551.1 2408.22   558.5 2409.74     561 2410.25     571 2416.13
   580.9 2420.43   590.8 2420.93   630.6 2439.29   640.5 2444.62   670.3 2463.89
   680.2 2464.41   729.9 2494.21   739.8 2499.26   749.8 2503.24   769.6 2509.36
   779.6 2509.64   789.5  2511.8     869 2535.39   888.9 2537.86   938.5 2552.22
#Mann= 3 , 0 , 0
       0      .1       0   546.5    .045       0   558.5      .1       0
Bank Sta=546.5,558.5
XS Rating Curve= 0 ,0
Exp/Cntr=0.3,0.1

Type RM Length L Ch R = 1 ,1109.7  ,1082.2,1109.3,1127.6
XS GIS Cut Line= 2
     1923973.499      122503.052     1924104.475      121588.726
#Sta/Elev= 30
       0 2422.57    89.4 2419.34   109.2  2418.9     149 2417.45   198.6 2413.62
   218.5 2412.91   248.3 2411.05     288    2409   317.8 2408.11   347.6    2408
   389.7    2408   401.7    2408   506.5 2408.13   546.2 2409.57     576 2409.93
   675.4 2409.59   695.2 2411.12   705.2 2412.77   715.1 2416.53     735 2424.44
   774.7  2441.2   784.6 2445.16   794.6 2447.84   804.5 2448.94   824.3 2456.16
   854.1 2466.46   883.9 2475.66   893.9 2478.31   903.8  2478.7   923.7  2484.9
#Mann= 3 , 0 , 0
       0      .1       0   389.7    .045       0   401.7      .1       0
Bank Sta=389.7,401.7
XS Rating Curve= 0 ,0
Exp/Cntr=0.3,0.1

Chan Stop Cuts=-1
Use User Specified Reach Order=0
Composite Channel Slope=5